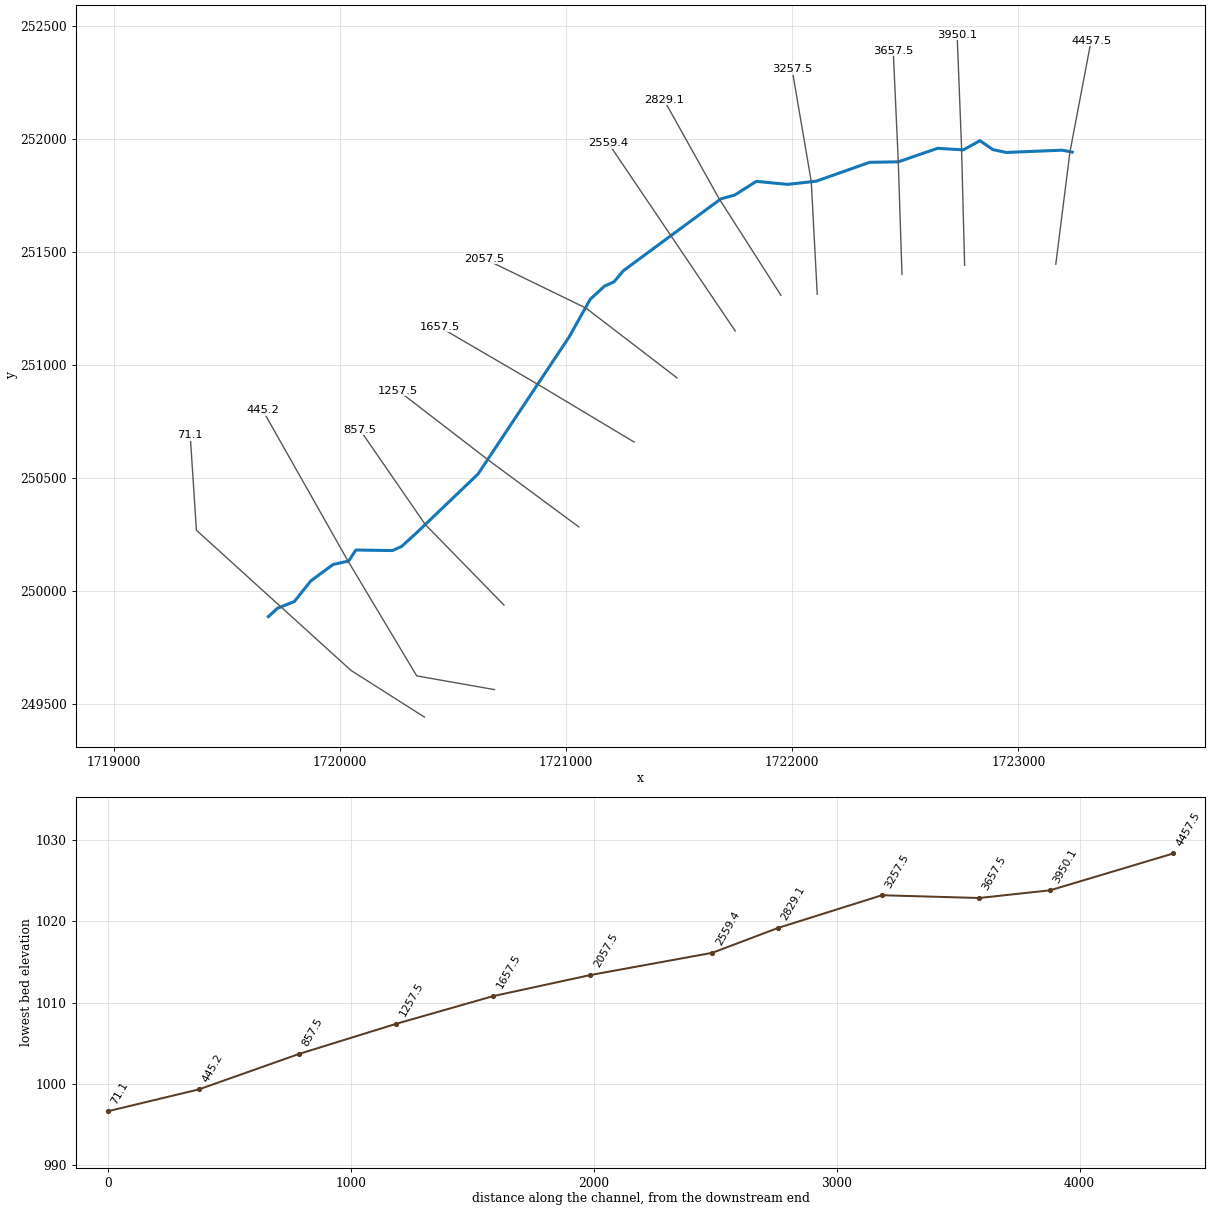
--- LostCrTr2.prj (project) ---

Proj Title=LostCrTr2
Current Plan=p01
Geom File=g01
Flow File=f01
Plan File=p01
DSS Export Rating Curves=0
DSS Export Rating Curve Sorted=0
DSS Export Volume Flow Curves=0
DXF OffsetX=0
DXF OffsetY=0
DXF ScaleX=0
DXF ScaleY=0

--- LostCrTr2.p01 (plan) ---

Plan Title=Floodplain
Program Version=4.00
Geom File=g01
Flow File=f01
K Sum by GR=0
Std Step Tol=0.01
Critical Tol=0.01
Num of Std Step Trials=20
Max Error Tol=0.3
Flow Tol Ratio=0.001
Split Flow NTrial=30
Split Flow Tol=0.02
Split Flow Ratio=0.02
Log Output Level=0
Friction Slope Method=1
Unsteady Friction Slope Method=2
Unsteady Bridges Friction Slope Method=1
Global Log Level=0
CheckData=False
Run HTab=0
Run UNet=0
Run PostProcess=0
UNET Theta=0
UNET Theta Warmup=0
UNET ZTol=0
UNET ZSATol=0
UNET MxIter=0
UNET MaxInSteps=0
UNET DtIC=0
UNET DtMin=0
UNET MaxCRTS=0
UNET WFStab=0
UNET SFStab=0
UNET WFX=0
UNET SFX=0
UNET DSS MLevel=0
UNET DZMax Abort=0
UNET Convert EG Bridges=0
UNET Use Existing IB Tables=0
UNET Froude Limit=0
UNET Froude Power=0
Write IC File=0
Echo Input=False
Echo Output=False
Write Detailed=0

--- LostCrTr2.f01 (steady flow) ---

Flow Title=NFF Regression Equation
Program Version=4.00
Number of Profiles=1
Profile Names=P100yr
River Rch & RM=LostCrTr2,Main      ,4457.5
889.1939
River Rch & RM=LostCrTr2,Main      ,2829.1
911.3237
River Rch & RM=LostCrTr2,Main      ,2559.4
1023.691
River Rch & RM=LostCrTr2,Main      ,71.1
1076.806
River Rch & RM=LostCrTr2,Main      ,71.1
3753.432
Boundary for River Rch & Prof#=LostCrTr2,Main      ,1
Up Type=0
Dn Type=3
Dn Slope=0.00777

--- LostCrTr2.g01 (geometry) ---

Geom Title=USGS 3m DEM
Program Version=4.00

River Reach=LostCrTr2     ,Main
Reach XY= 30
     1723238.688      251943.045     1723193.948      251951.556
     1722946.963      251941.420     1722888.420      251953.845
     1722830.365      251993.424     1722756.875      251952.874
     1722643.057      251959.829     1722469.577      251899.985
     1722342.362      251897.826     1722106.064      251814.276
     1721979.071      251800.191     1721841.372      251813.606
     1721745.754      251752.975     1721684.639      251736.298
     1721252.753      251417.977     1721211.557      251368.995
     1721169.348      251350.051     1721106.599      251291.868
     1721012.583      251124.496     1720609.765      250518.487
     1720336.364      250256.996     1720272.050      250198.472
     1720231.477      250180.294     1720069.647      250182.707
     1720037.718      250133.896     1719968.788      250118.627
     1719870.286      250046.078     1719797.530      249954.728
     1719723.297      249925.329     1719682.803      249888.200

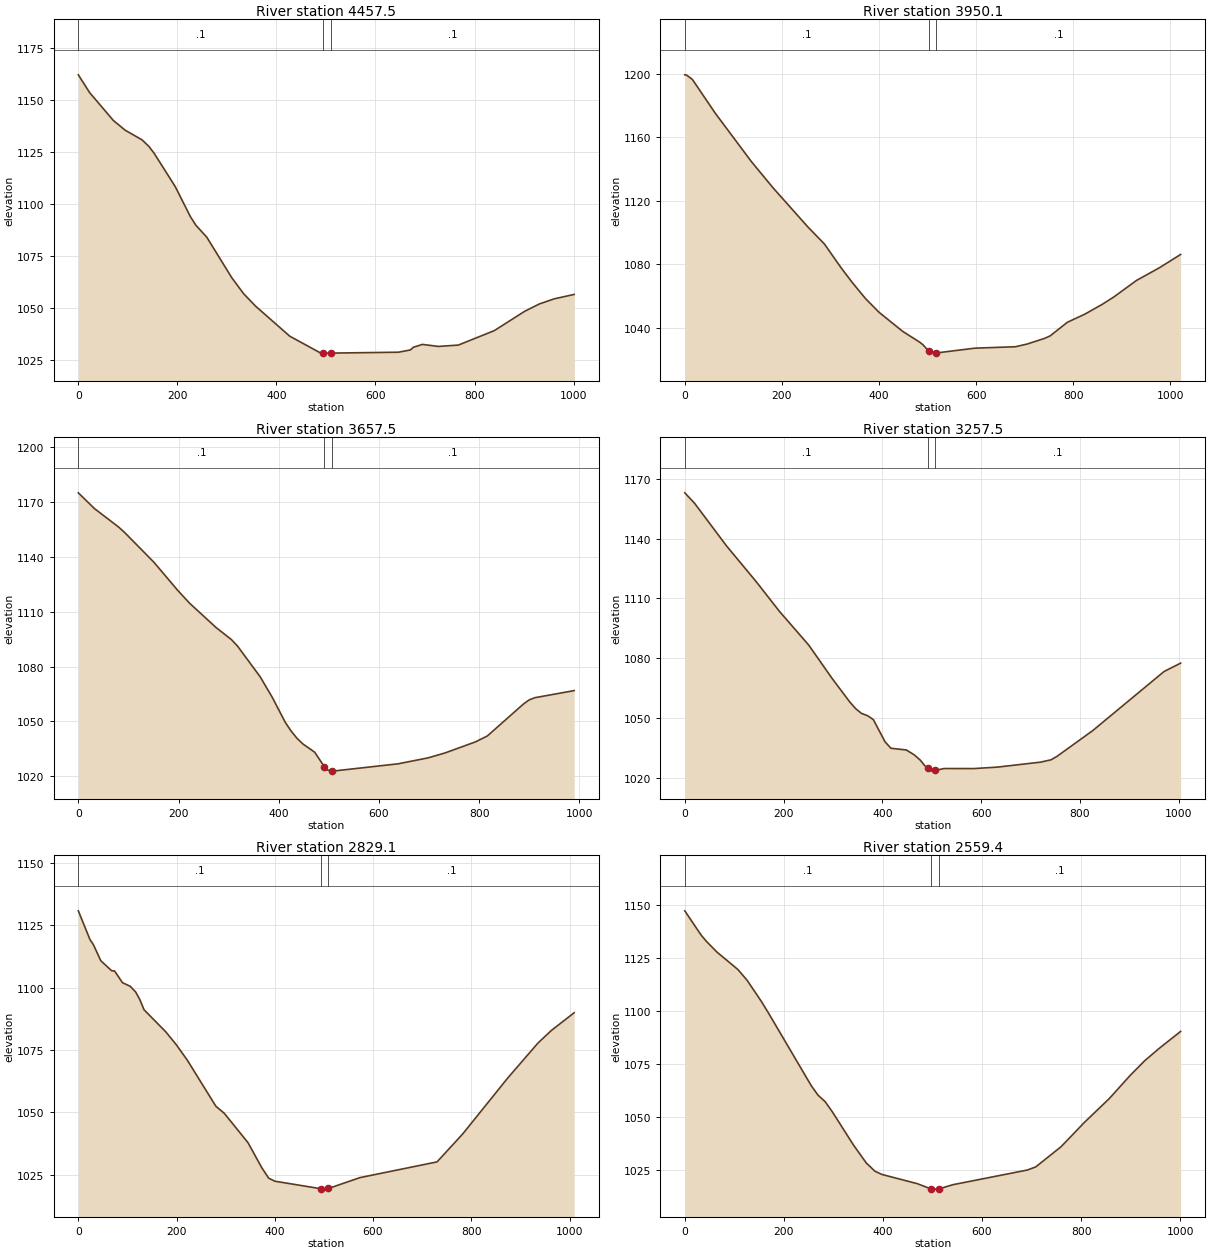
Type RM Length L Ch R = 1 ,4457.5,504.335,507.394,511.884
XS GIS Cut Line= 3
     1723166.067      251447.170     1723228.864      251944.914
     1723322.367      252436.388
#Sta/Elev= 30
       0 1162.21    22.8 1153.67    70.7 1140.27    94.6 1135.59   128.8 1130.91
   142.5 1127.78   153.1 1124.48   195.6 1108.51   226.2 1094.06   237.3 1089.90
   259.4 1084.13   310.0 1064.60   333.9 1056.93   357.9 1050.98   427.0 1036.52
   489.5 1028.41   494.2 1028.41   501.5 1028.39   509.2 1028.40   646.5 1028.83
   670.7 1029.94   676.3 1031.19   694.8 1032.58   727.0 1031.61   767.3 1032.26
   839.9 1039.20   901.2 1048.49   931.1 1052.05   960.7 1054.48  1001.2 1056.61
#Mann= 3 , 0 , 0
       0     0.1       0   494.2   0.045       0   509.2     0.1       0
Bank Sta=   494.2,   509.2
Exp/Cntr=0.3,0.1

Type RM Length L Ch R = 1 ,3950.1,292.501,292.606,292.955
XS GIS Cut Line= 3
     1722762.742      251442.214     1722748.787      251972.998
     1722729.558      252462.647
#Sta/Elev= 30
       0 1199.47     3.8 1199.29    15.7 1196.54    63.2 1175.05   137.1 1144.73
   182.0 1128.06   253.2 1103.55   287.6 1092.69   322.3 1077.51   345.4 1068.21
   372.0 1058.30   400.0 1049.61   448.8 1037.55   484.3 1030.63   490.8 1029.02
   502.7 1024.95   514.5 1023.84   517.7 1023.93   597.7 1026.98   680.9 1027.87
   704.6 1029.54   740.3 1033.09   752.2 1034.69   787.8 1043.31   823.5 1048.39
   859.1 1054.54   882.9 1059.15   930.0 1069.68   977.9 1077.82  1021.0 1086.11
#Mann= 3 , 0 , 0
       0     0.1       0   502.7   0.045       0   517.7     0.1       0
Bank Sta=   502.7,   517.7
Exp/Cntr=0.3,0.1

Type RM Length L Ch R = 1 ,3657.5,399.545,400,402.82
XS GIS Cut Line= 3
     1722485.608      251401.827     1722469.299      251900.000
     1722446.956      252390.768
#Sta/Elev= 30
       0 1174.88    32.4 1166.23    79.9 1156.31    91.8 1153.39   151.2 1136.88
   198.7 1121.51   222.4 1114.52   275.0 1101.30   305.6 1094.72   317.5 1091.28
   362.8 1074.49   387.3 1063.10   413.0 1049.58   424.4 1044.90   436.0 1040.96
   448.1 1037.76   471.9 1033.20   490.9 1025.37   495.6 1023.62   505.9 1022.97
   507.5 1022.89   638.3 1026.88   697.7 1030.10   732.3 1032.85   792.8 1038.87
   816.5 1042.11   887.8 1059.38   899.7 1061.76   911.6 1063.01   989.7 1066.87
#Mann= 3 , 0 , 0
       0     0.1       0   490.9   0.045       0   505.9     0.1       0
Bank Sta=   490.9,   505.9
Exp/Cntr=0.3,0.1

Type RM Length L Ch R = 1 ,3257.5,416.637,428.395,436.581
XS GIS Cut Line= 3
     1722110.767      251314.036     1722084.264      251813.118
     1721999.146      252310.437
#Sta/Elev= 30
       0 1163.08    19.6 1157.90    84.6 1136.38   144.1 1118.60   191.6 1103.54
   251.1 1086.54   298.6 1069.71   334.3 1057.92   346.2 1054.60   357.9 1052.23
   370.5 1051.05   381.9 1049.10   405.6 1037.94   417.5 1034.72   448.6 1033.87
   465.1 1031.34   477.0 1028.72   488.9 1025.07   492.3 1024.56   500.8 1023.23
   507.3 1023.57   524.9 1024.54   585.1 1024.51   633.3 1025.25   720.5 1027.75
   741.7 1028.92   753.7 1030.64   826.0 1043.57   970.5 1073.28  1004.1 1077.50
#Mann= 3 , 0 , 0
       0     0.1       0   492.3   0.045       0   507.3     0.1       0
Bank Sta=   492.3,   507.3
Exp/Cntr=0.3,0.1

Type RM Length L Ch R = 1 ,2829.1,269.061,269.644,271.18
XS GIS Cut Line= 3
     1721950.074      251309.556     1721675.767      251738.335
     1721431.919      252175.291
#Sta/Elev= 30
       0 1130.83    23.8 1119.27    30.7 1117.25    45.8 1110.80    67.8 1106.80
    73.7 1106.72    89.9 1102.01   105.6 1100.56   116.7 1098.29   125.3 1095.20
   133.8 1091.14   178.0 1082.30   200.0 1076.98   222.0 1070.88   280.0 1052.45
   297.2 1049.59   345.3 1037.86   373.4 1027.82   387.5 1023.58   400.3 1022.36
   494.2 1019.34   500.3 1019.19   509.2 1019.45   573.2 1023.80   730.3 1030.12
   782.6 1041.35   873.8 1063.67   935.7 1077.79   962.9 1082.82  1009.4 1089.95
#Mann= 3 , 0 , 0
       0     0.1       0   494.2   0.045       0   509.2     0.1       0
Bank Sta=   494.2,   509.2
Exp/Cntr=0.3,0.1

Type RM Length L Ch R = 1 ,2559.4,494.635,501.961,513.929
XS GIS Cut Line= 3
     1721747.929      251151.707     1721467.885      251566.527
     1721187.841      251981.347
#Sta/Elev= 30
       0 1147.17    32.9 1135.77    43.5 1132.83    64.8 1127.78   107.2 1119.54
   125.9 1114.44   154.6 1104.50   168.9 1099.08   255.7 1064.69   269.2 1060.33
   283.5 1057.28   298.2 1052.42   340.6 1036.88   366.4 1028.45   383.8 1024.57
   398.1 1023.03   469.0 1018.73   497.2 1016.22   510.4 1016.13   512.2 1016.19
   541.4 1018.22   691.3 1025.11   708.5 1026.59   759.8 1036.13   807.4 1047.71
   856.5 1058.65   899.5 1069.76   928.1 1076.50   956.0 1082.08  1001.0 1090.39
#Mann= 3 , 0 , 0
       0     0.1       0   497.2   0.045       0   512.2     0.1       0
Bank Sta=   497.2,   512.2
Exp/Cntr=0.3,0.1

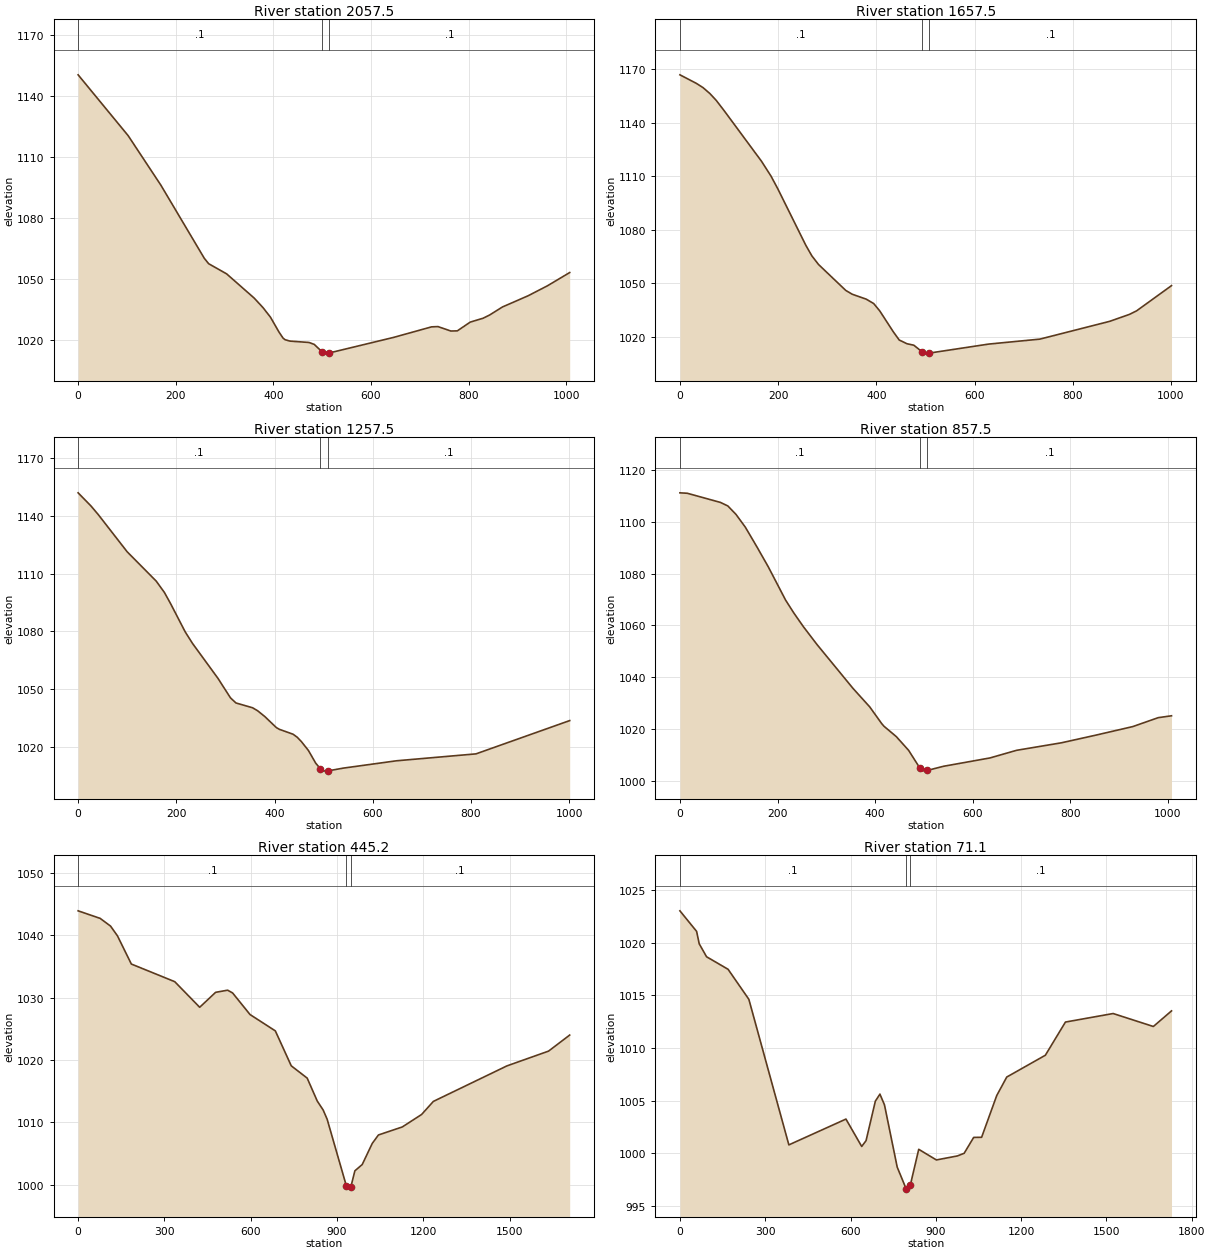
Type RM Length L Ch R = 1 ,2057.5,397.317,400,398.293
XS GIS Cut Line= 3
     1721490.088      250944.486     1721087.797      251252.872
     1720637.893      251471.374
#Sta/Elev= 30
       0 1150.52   102.4 1120.58   169.6 1096.12   258.5 1060.11   267.4 1057.45
   304.2 1052.45   360.6 1040.53   379.0 1035.74   394.0 1031.11   411.4 1023.81
   419.9 1020.77   423.9 1020.01   434.1 1019.31   473.1 1018.64   483.7 1017.69
   499.4 1014.12   512.8 1013.39   514.4 1013.47   646.6 1021.16   724.0 1026.33
   737.2 1026.46   763.6 1024.28   776.8 1024.36   803.2 1028.67   829.6 1030.59
   842.8 1032.15   869.2 1036.13   921.9 1041.66   961.6 1046.59  1007.0 1053.10
#Mann= 3 , 0 , 0
       0     0.1       0   499.4   0.045       0   514.4     0.1       0
Bank Sta=   499.4,   514.4
Exp/Cntr=0.3,0.1

Type RM Length L Ch R = 1 ,1657.5,402.173,400,397.115
XS GIS Cut Line= 3
     1721300.985      250660.172     1720871.687      250917.457
     1720439.344      251169.691
#Sta/Elev= 30
       0 1166.89    33.3 1162.13    47.2 1159.68    61.0 1156.39    73.7 1152.63
    88.7 1147.29   166.1 1118.42   185.6 1110.03   199.4 1102.92   256.2 1071.37
   268.6 1065.38   282.1 1060.55   337.8 1045.94   350.9 1043.82   379.4 1041.06
   394.6 1038.60   407.0 1034.44   434.7 1022.68   446.6 1018.14   462.4 1016.05
   476.3 1015.24     493 1011.53   503.9 1010.79     508 1010.82   628.7 1015.86
   732.9 1018.64   875.0 1028.61   915.2 1032.50   930.0 1034.52  1001.0 1048.65
#Mann= 3 , 0 , 0
       0     0.1       0     493   0.045       0     508     0.1       0
Bank Sta=     493,     508
Exp/Cntr=0.3,0.1

Type RM Length L Ch R = 1 ,1257.5,403.638,400,392.952
XS GIS Cut Line= 3
     1721055.937      250285.026     1720653.214      250582.664
     1720256.687      250888.072
#Sta/Elev= 30
       0 1152.10    26.1 1145.29    40.9 1140.82    99.9 1121.44   159.0 1106.20
   175.6 1100.34   188.5 1094.40   218.0 1079.84   232.8 1073.85   284.9 1055.59
   310.3 1045.48   321.4 1042.83   355.4 1040.31   365.7 1038.75   380.4 1035.71
   403.7 1030.02   409.9 1029.11   437.7 1026.57   446.2 1025.01   454.7 1022.73
   469.0 1018.13   483.8 1011.56   493.3 1008.62   497.1 1007.58   505.6 1007.37
   508.3 1007.47   539.4 1008.91   648.3 1012.74   810.3 1016.34  1001.2 1033.65
#Mann= 3 , 0 , 0
       0     0.1       0   493.3   0.045       0   508.3     0.1       0
Bank Sta=   493.3,   508.3
Exp/Cntr=0.3,0.1

Type RM Length L Ch R = 1 ,857.5,417.644,412.262,410.174
XS GIS Cut Line= 3
     1720724.911      249939.126     1720376.209      250296.232
     1720087.627      250714.748
#Sta/Elev= 30
       0 1111.17    15.1 1111.00    83.0 1107.47    98.3 1106.09   114.9 1102.84
   134.0 1097.92   157.9 1090.27   181.3 1082.51   216.7 1069.69   233.5 1064.74
   253.0 1059.47   280.8 1052.60   354.9 1035.58   388.9 1028.50   413.6 1022.00
   418.2 1020.99   443.4 1017.00   468.6 1011.71   491.6 1004.89   496.6 1004.01
   502.2 1003.65   506.6 1003.90   540.2 1005.52   635.4 1008.74   690.0 1011.69
   781.8 1014.59   852.2 1017.54   928.2 1020.86   980.2 1024.30  1007.5 1025.03
#Mann= 3 , 0 , 0
       0     0.1       0   491.6   0.045       0   506.6     0.1       0
Bank Sta=   491.6,   506.6
Exp/Cntr=0.3,0.1

Type RM Length L Ch R = 1 ,445.2,366.428,374.111,382.357
XS GIS Cut Line= 4
     1720682.893      249565.160     1720339.038      249625.841
     1720035.589      250132.877     1719657.107      250801.883
#Sta/Elev= 30
       0 1043.95    76.5 1042.74   112.7 1041.50   136.8 1039.93   185.0 1035.41
   335.8 1032.58   422.6 1028.47   478.0 1030.87   519.7 1031.21   537.0 1030.77
   597.6 1027.30   685.5 1024.68   740.9 1019.07   796.2 1017.10   831.3 1013.41
   851.6 1011.99   865.4 1010.53   932.7  999.75   943.8  999.28   947.7  999.58
   962.0 1002.22   987.4 1003.22  1022.2 1006.60  1043.8 1007.97  1126.8 1009.26
  1193.9 1011.26  1234.8 1013.36  1490.5 1019.06  1635.1 1021.43  1708.7 1024.01
#Mann= 3 , 0 , 0
       0     0.1       0   932.7   0.045       0   947.7     0.1       0
Bank Sta=   932.7,   947.7
Exp/Cntr=0.3,0.1

Type RM Length L Ch R = 1 ,71.1,74.853,71.106,67.359
XS GIS Cut Line= 4
     1720372.888      249443.675     1720048.285      249649.979
     1719364.350      250270.031     1719336.872      250690.408
#Sta/Elev= 30
       0 1023.01    58.7 1021.06    67.9 1019.88    93.7 1018.65   169.4 1017.46
   242.5 1014.61   383.2 1000.79   584.0 1003.24   639.4 1000.64   654.7 1001.19
   687.4 1004.94   703.5 1005.61   719.5 1004.59   764.3  998.68   795.4  996.64
   797.9  996.59   810.4  996.97   840.0 1000.37   902.1  999.36   975.9  999.74
   999.7  999.99  1033.3 1001.50  1061.2 1001.51  1114.3 1005.47  1149.6 1007.23
  1285.4 1009.30  1356.0 1012.45  1523.8 1013.26  1665.3 1012.03  1729.1 1013.51
#Mann= 3 , 0 , 0
       0     0.1       0   795.4   0.045       0   810.4     0.1       0
Bank Sta=   795.4,   810.4
Exp/Cntr=0.3,0.1